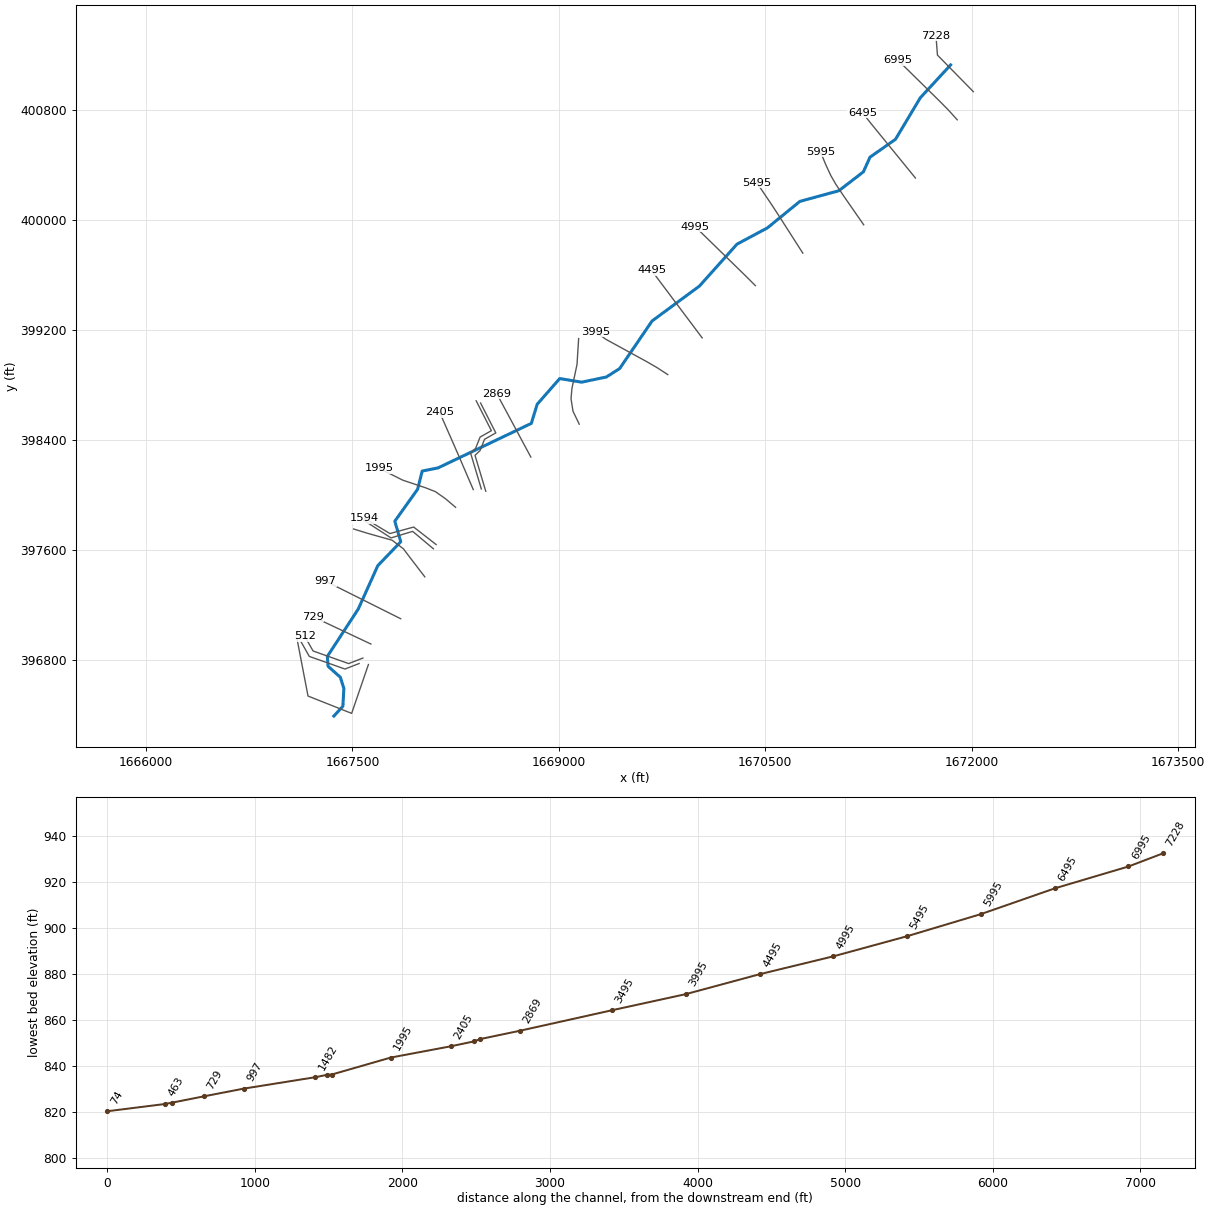
--- RCKCMPRN2.prj (project) ---

Proj Title=RCKCMPRN2
Current Plan=p01
Default Exp/Contr=0,0
English Units
Geom File=g01
Flow File=f01
Plan File=p01
BEGIN DESCRIPTION:
---------- MODELED AS PART OF WVEMD CTP PROGRAM, 2023----------
Stream Name: Rockcamp Run (II)
Flood Zone:  AFH
Wetzel County, WV
HEC-RAS Version: RAS 6.3
Vertical Datum: NAVD88
Projection: NAD 1983 StatePlane West Virginia S FIPS 4702 (US Feet)
Terrain: 1-meter West Virginia FEMA R3 South Central (collected 2018-2020)
Land Use: 2019 NLCD
Hydrologic Method:
WV 2010 Regional Regression Equations
Additional Model Notes:
None
END DESCRIPTION:
DSS Export Rating Curves= 0
DSS Export Rating Curve Sorted= 0
DSS Export Volume Flow Curves= 0
DXF OffsetX= 0
DXF OffsetY= 0
DXF ScaleX= 0
DXF ScaleY= 0

--- RCKCMPRN2.p01 (plan) ---

Plan Title=Floodplain
Program Version=6.30
Short Identifier=Floodplain
Geom File=g01
Flow File=f01
Subcritical Flow
K Sum by GR= 0
Std Step Tol= 0.01
Critical Tol= 0.01
Num of Std Step Trials= 20
Max Error Tol= 0.3
Flow Tol Ratio= 0.001
Split Flow NTrial= 30
Split Flow Tol= 0.02
Split Flow Ratio= 0.02
Log Output Level= 0
Friction Slope Method= 1
Unsteady Friction Slope Method= 2
Unsteady Bridges Friction Slope Method= 1
Parabolic Critical Depth
Global Vel Dist= 0 , 0 , 0
Global Log Level= 0
CheckData=False
Encroach Param=-1 ,0,0, 0
Mapping Interval=1HOUR
Computation Time Step Use Courant=        0
Computation Time Step Use Time Series=    0
Computation Time Step Count To Double=0
Computation Time Step Max Doubling=0
Computation Time Step Max Halving=0
Computation Time Step Residence Courant=0
Run HTab= 0
Run UNet= 0
Run Sediment= 0
Run PostProcess= 0
Run WQNet= 0
Run RASMapper=-1
UNET Theta= 0
UNET Theta Warmup= 0
UNET ZTol= 0
UNET ZSATol= 0
UNET MxIter= 0
UNET Max Iter WO Improvement= 0
UNET MaxInSteps= 0
UNET DtIC= 0
UNET DtMin= 0
UNET MaxCRTS= 0
UNET WFStab= 0
UNET SFStab= 0
UNET WFX= 1
UNET SFX= 1
UNET Gravity=32.17405
UNET 1D Methodology=Finite Difference
UNET DSS MLevel= 1
UNET Pardiso=0
UNET DZMax Abort= 0
UNET Use Existing IB Tables= 0
UNET Froude Reduction=False
UNET Froude Limit= 0
UNET Froude Power= 0
UNET D1 Cores= 0
UNET WindReference=Eulerian
UNET WindDragFormulation=Hsu (1988)
UNET D2 Coriolis=0
UNET D2 Cores= 0
UNET D2 Theta= 1
UNET D2 Theta Warmup= 1
UNET D2 Z Tol= 0.01
UNET D2 Volume Tol= 0.01
UNET D2 Max Iterations= 20
UNET D2 Equation= 0
UNET D2 RampUpFraction=0.1
UNET D2 TimeSlices= 1
UNET D2 Turbulence Formulation=Non-Conservative (original)
UNET D2 Eddy Viscosity=0.3
UNET D2 Transverse Eddy Viscosity=0.1
UNET D2 Smagorinsky Mixing=0
UNET D2 BCVolumeCheck=0
UNET D2 Cores=0
UNET D2 SolverType=PARDISO (Direct)
UNET D2 Minimum Iterations= 3
UNET D2 Maximum Iterations= 30
UNET D2 Restart Number= 10
UNET D2 Relaxation Coeff=1.3
UNET D2 SOR Precondition Iterations= 10
UNET D2 ILUT Maximum Fill= 8
UNET D2 ILUT Tolerance=1E-08
UNET D2 Convergence Tolerance=0.00001
UNET D1D2 MaxIter= 0
UNET D1D2 ZTol=0.01
UNET D1D2 QTol=0.1
UNET D1D2 MinQTol=1
Write IC File= 0
Write IC File at Fixed DateTime=0
Write IC File at Sim End=0
Echo Input=False
Echo Parameters=False
Echo Output=False
Write Detailed= 0
HDF Write Warmup=0
HDF Write Time Slices=0
HDF Flush=0
HDF Compression= 1
HDF Chunk Size= 1
HDF Spatial Parts= 1
HDF Use Max Rows=0
HDF Fixed Rows= 1
Calibration Method= 0
Calibration Iterations= 20
Calibration Max Change=0.05
Calibration Tolerance=0.2
Calibration Maximum=1.5
Calibration Minimum=0.5
Calibration Optimization Method= 1
WQ AD Non Conservative
WQ ULTIMATE=-1
WQ Max Comp Step=1HOUR
WQ Output Interval=15MIN
WQ Output Selected Increments= 0
WQ Output face flow=0
WQ Output face velocity=0
WQ Output face area=0
WQ Output face dispersion=0
WQ Output cell volume=0
WQ Output cell surface area=0
WQ Output cell continuity=0
WQ Output cumulative cell continuity=0
WQ Output face conc=0
WQ Output face dconc_dx=0
WQ Output face courant=0
WQ Output face peclet=0
WQ Output face adv mass=0
WQ Output face disp mass=0
WQ Output cell mass=0
WQ Output cell source sink temp=0
WQ Output nsm pathways=0
WQ Output nsm derived pathways=0
WQ Create Restart=0
WQ Fixed Restart=0
WQ System Summary=0
WQ Write To DSS=0
Sorting and Armoring Iterations= 10
XS Update Threshold= 0.02
Bed Roughness Predictor= 0
Hydraulics Update Threshold= 0.02
Energy Slope Method= 1
Volume Change Method= 1
Sediment Retention Method= 0
Sediment TS Multiplier= 1
Warm Up Method= 0
XS Weighting Method= 0
Number of US Weighted Cross Sections= 1
Number of DS Weighted Cross Sections= 1
Upstream XS Weight=0
Main XS Weight=1
Downstream XS Weight=0
Number of DS XS's Weighted with US Boundary= 1
Upstream Boundary Weight= 1
Weight of XSs Associated with US Boundary= 0
Number of US XS's Weighted with DS Boundary= 1
Downstream Boundary Weight= 0.5
Weight of XSs Associated with DS Boundary= 0.5
Percentile Method= 0
Sediment Output Level= 3
Mass or Volume Output= 0
Output Increment Type= 1
Profile and TS Output Increment= 1
Transport Output Increment 1
XS Output Flag= 0
XS Output Increment= 10
Read HDF5 Sediment Hotstart= 0
Sediment Hotstart Type= 0
Write Gradation File= 0
Read Gradation Hotstart= 0
Write HDF5 File= 1
Write Binary Output= 1
Write DSS Sediment File= 0
DSS Sediment Output Type= 1
SV Curve= 0
Specific Gage Flag= 0
Subcell Erosion Methods= 0
Subcell Deposition Methods= 0
Advection Scheme= 1
Matrix Solver= 0
Implicit Weighting Factor= 1
Maximum Outer Loop Convergence Iterations= 5
Convergence Maximum Absolute= 0.001
Convergence RMSE= 0.0001
Grain Fractions Max Abs Error= 0.001
Max Subgrid Regions= 1
Max Subgrid Length Scale= 3.402823E+38
Initial Layer Thickness= 3.402823E+38
Min Layer Thickness= 3.402823E+38
Max Layer Thickness= 3.402823E+38
Number of Layers= 5

--- RCKCMPRN2.f01 (steady flow) ---

Flow Title=Flow
Program Version=6.31
Number of Profiles= 1
Profile Names=F01pct
River Rch & RM=RCKCMPRN2,Main,7228
     742
River Rch & RM=RCKCMPRN2,Main,3995
     838
Boundary for River Rch & Prof#=RCKCMPRN2,Main            , 1
Up Type= 0
Dn Type= 3
Dn Slope=0.00801
DSS Import GetInterval= 0
DSS Import GetPeak= 0
DSS Import FillOption= 0

--- RCKCMPRN2.g01 (geometry) ---

Geom Title=Geometry
Program Version=6.30

River Reach=RCKCMPRN2       ,Main
Reach XY= 30
1671846.82718985401126.886091988     1671626.905      400888.596
     1671445.962      400586.231     1671261.278      400456.646
     1671212.642      400349.849      1671034.76      400212.782
     1670751.782      400135.575       1670515.4      399942.728
     1670294.323      399824.367     1670021.208      399519.621
     1669677.349      399266.233     1669441.647      398920.333
     1669345.054      398859.112     1669165.471      398821.699
     1669006.296      398847.888     1668842.699      398661.164
     1668799.844      398522.0551668122.18977006398198.663494616
     1668007.029      398175.815     1667974.038      398044.189
      1667808.06      397811.209     1667851.255      397662.237
     1667684.257      397488.096     1667542.768      397173.827
      1667317.61      396828.608     1667323.052      396757.183
     1667412.163      396677.255     1667437.672      396595.967
1667430.62579468396466.480698446     1667365.003      396395.183

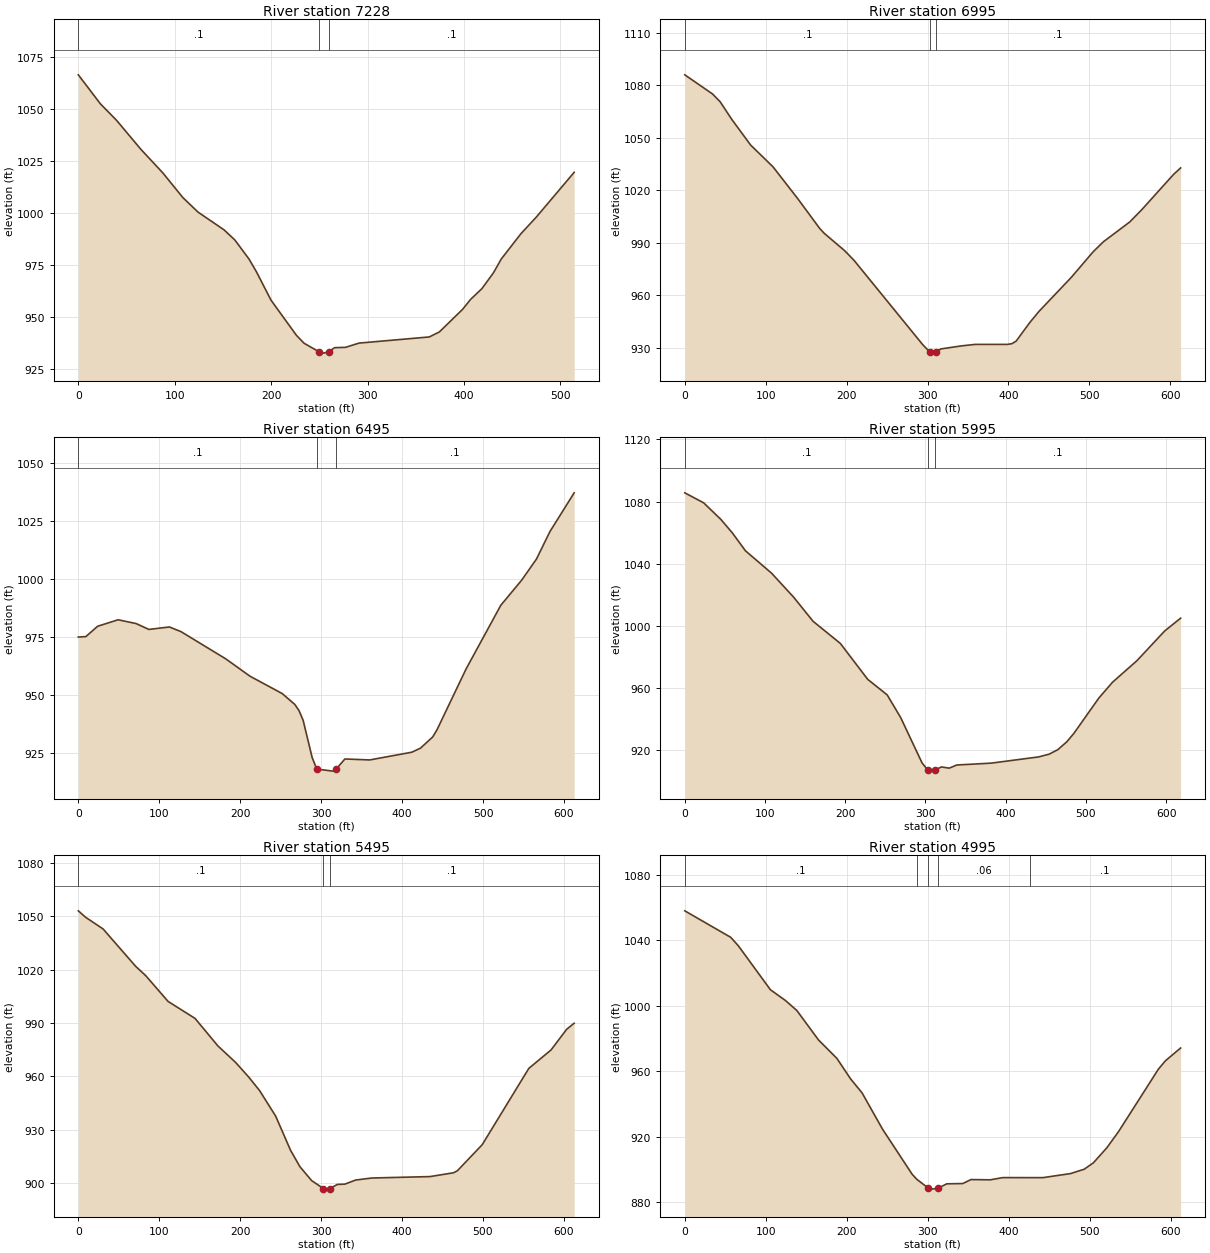
Type RM Length L Ch R = 1 ,7228    ,233.2,233.2,233.2
XS GIS Cut Line= 3
1672012.14340242400932.7268719441671751.24717083401198.499668604
1671740.27489941401339.920055817
#Sta/Elev= 30
       0 1066.55    22.9 1052.58    39.5 1044.73    64.9 1030.68    87.6 1019.37
   108.5 1007.42   124.3 1000.41   151.1  991.94   162.3  987.09   177.1  977.83
   184.7  971.77   199.9  958.06   226.2  941.17   234.2  937.32   249.2933.3572
   254.5  932.58   260.1  933.36   265.8   935.2   277.1  935.36   291.2  937.41
   364.1  940.37   374.5  942.79   398.5  953.62     407  958.51   418.6  963.61
   430.6  971.25   438.7   977.9   459.1  990.07   474.8  997.94   514.3 1019.62
#Mann= 3 ,-1,0
       0      .1       0   249.2    .045       0   260.1      .1       0
Bank Sta=249.2,260.1
XS Rating Curve= 0 ,0
Exp/Cntr(USF)=0,0
Exp/Cntr=0.3,0.1

Type RM Length L Ch R = 1 ,6995    ,500,500,500
XS GIS Cut Line= 6
  1671895.067495400728.1204297541671832.13750276400797.799424261
1671770.76164126400860.1805330961671592.45392701401035.413122252
1671530.04689959401096.7450205831671463.18121967401162.456831425
#Sta/Elev= 30
       0 1086.06    34.2 1075.14    43.7 1070.66    58.1 1060.55    81.4 1045.87
     109 1033.45   139.6 1015.23   166.6  998.27   172.2  995.46   197.7  985.42
     209  980.03   293.8  931.85   302.9  927.44   307.5  926.89   310.1927.4404
   316.5   929.3   341.7  931.02   358.9  931.88   398.8  931.89   404.2   932.3
   409.4  933.72   426.3  944.37   437.5  950.67   477.7  970.27   504.8  984.95
   517.3  990.59   549.7 1001.86   564.3 1008.73   604.2 1029.21   612.7 1032.81
#Mann= 3 ,-1,0
       0      .1       0   302.9    .045       0   310.1      .1       0
Bank Sta=302.9,310.1
XS Rating Curve= 0 ,0
Exp/Cntr(USF)=0,0
Exp/Cntr=0.3,0.1

Type RM Length L Ch R = 1 ,6495    ,499.2,499.2,499.2
XS GIS Cut Line= 6
1671591.22656725400305.3030339181671429.29217984400503.901390001
 1671366.0980805400581.4032035021671318.70316218400639.529727668
1671263.40898143400707.3442245871671205.72504167400781.274194837
#Sta/Elev= 30
       0  975.04     9.3  975.23    23.9  979.69    49.2  982.46    71.3  980.84
    87.2  978.31   112.5  979.37   126.8  977.37   182.2  965.64   212.1  958.19
   251.9  950.72   267.4  946.06   272.6  943.42   277.7  939.24   288.8  923.27
   294.5  918.26   314.4  917.37   318.5918.2533   329.3   922.6   359.9  922.18
   411.9   925.5   422.7  927.26   437.7  932.05   442.9  935.03     479  961.31
   521.9   988.7   547.6  999.47   565.9 1008.55   582.6 1020.41   612.5 1037.06
#Mann= 3 ,-1,0
       0      .1       0   294.5    .045       0   318.5      .1       0
Bank Sta=294.5,318.5
XS Rating Curve= 0 ,0
Exp/Cntr(USF)=0,0
Exp/Cntr=0.3,0.1

Type RM Length L Ch R = 1 ,5995    ,500.8,500.8,500.8
XS GIS Cut Line= 6
1671215.25881526399965.2754987631671069.09604985400175.752768084
1671013.34681751400258.8123132591670975.47517408400324.776420176
1670938.04250617400406.0164151791670901.18037517400494.891237423
#Sta/Elev= 30
       0 1085.61    23.5 1079.16    44.8 1068.56    59.2 1059.84    75.6 1048.24
   108.1 1033.84   135.5 1018.44   159.8 1002.84   193.9  988.52     228  965.38
   252.3  955.33   269.1  940.72   295.7  911.53     303 906.796   305.4  906.21
   311.4906.7585   319.8  908.91   329.5  908.14   339.1  910.16   381.9  911.36
   440.9  915.36   454.1  917.14   464.9  920.03   476.1   925.1   484.9   930.5
   516.1  953.34   533.2  963.56   563.5  977.39   598.1  996.54     618 1004.81
#Mann= 3 ,-1,0
       0      .1       0     303    .045       0   311.4      .1       0
Bank Sta=303,311.4
XS Rating Curve= 0 ,0
Exp/Cntr(USF)=0,0
Exp/Cntr=0.3,0.1

Type RM Length L Ch R = 1 ,5495    ,500,500,500
XS GIS Cut Line= 6
1670772.97984417399759.1456616671670722.40940726399838.086776748
1670580.80831251400059.1194711771670539.62893292400121.808978334
 1670490.5683355 400194.295053841670438.06811242400272.141354844
#Sta/Elev= 30
       0 1053.05       9 1049.42    30.6 1042.86    71.1 1021.72    83.2 1016.66
   110.9 1002.12   144.2  992.58   172.5  977.09   194.4  967.81   210.7  959.52
   224.1  951.92   243.9  937.59   262.2  918.48   273.8  909.22   288.3  901.38
   302.8  896.93   305.7  896.59   311.2896.9255   319.9  899.22   329.4   899.4
   342.7   901.7   362.7  902.84   434.5  903.64   463.5  905.77   468.4  906.91
   499.1  921.58   556.7  964.48   584.2  974.86   603.5  986.49   612.7  989.85
#Mann= 3 ,-1,0
       0      .1       0   302.8    .045       0   311.2      .1       0
Bank Sta=302.8,311.2
XS Rating Curve= 0 ,0
Exp/Cntr(USF)=0,0
Exp/Cntr=0.3,0.1

Type RM Length L Ch R = 1 ,4995    ,500,500,500
XS GIS Cut Line= 6
1670428.25120293399523.0044016691670361.96491817399589.310371429
1670299.35152633399650.431640252  1670174.126055 399772.67549026
1670057.84577575399886.1883865891669990.75995192399951.675460339
#Sta/Elev= 30
       0 1058.09    56.8 1041.86    66.2 1036.67   105.8  1009.8   124.3 1003.25
   138.5  997.07   165.2  979.08   187.9  967.82   204.8  955.29     219  946.71
   244.4  924.41   280.8  896.98   286.4  893.94     301  888.41   304.5  887.84
     313888.4015   323.6  891.08   343.4  891.25   353.5  893.69   377.4  893.53
   392.6  894.88   442.4  894.87   476.5  897.35   493.4  900.01   504.7  903.92
   521.2  913.03   535.8  923.01   585.1  961.27   593.8  966.39   612.5  974.17
#Mann= 5 ,-1,0
       0      .1       0  286.26     .06       0     301    .045       0
     313     .06       0  426.26      .1       0
Bank Sta=301,313
XS Rating Curve= 0 ,0
Exp/Cntr(USF)=0,0
Exp/Cntr=0.3,0.1

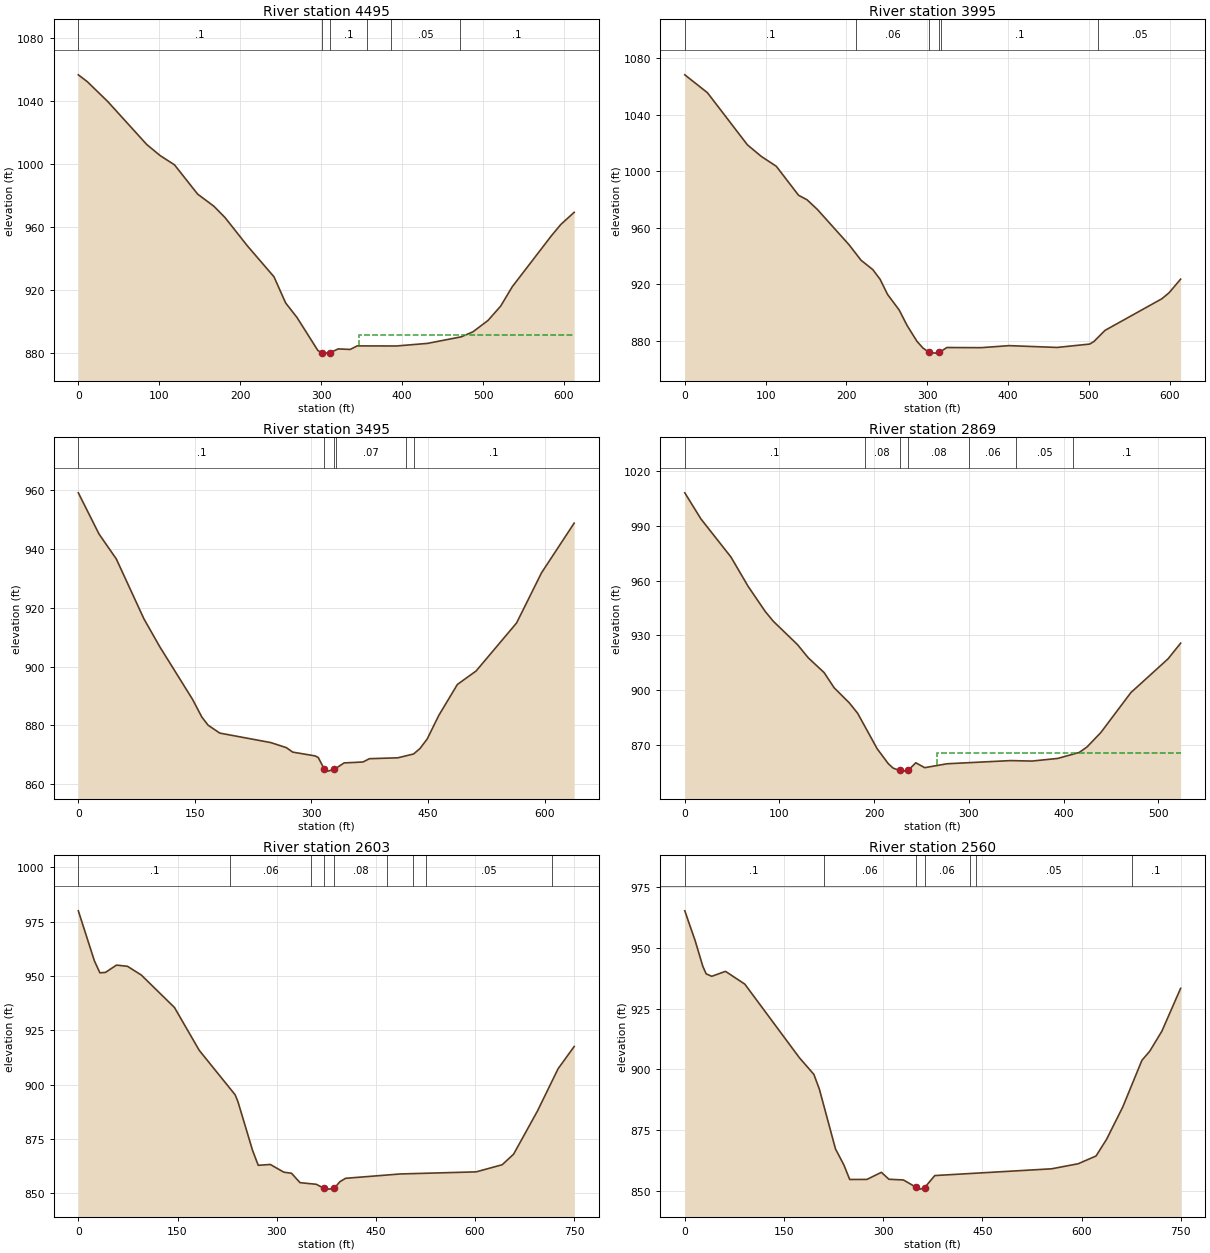
Type RM Length L Ch R = 1 ,4495    ,500,500,500
XS GIS Cut Line= 6
1670041.51017851399143.6170370881669887.76048601399348.617611334
1669827.76060601 399428.617451341669782.76102409399488.617987499
  1669730.260801399558.6178475021669674.01124159399633.618025586
#Sta/Elev= 30
       0 1056.72    11.2 1052.32    36.2 1039.85    84.5  1012.5   101.1 1005.44
   118.8  999.59   147.4     981   167.4  973.33   181.3  966.07     209  948.05
   241.7  928.52   256.1  911.92   270.2  902.64   295.9  881.74   300.7  880.37
   306.1  880.06   311.1  880.36   321.1  882.74   335.7  882.39   344.5  884.65
   393.1   884.6   431.3  886.24   473.1  890.42   487.4  893.56   506.1  900.81
   521.7   909.9   536.1  922.25   584.5  954.63   596.1  961.77   612.5  969.44
#Mann= 6 ,-1,0
       0      .1       0   300.7    .045       0   311.1      .1       0
  356.25     .06       0  386.25     .05       0  471.25      .1       0
#XS Ineff= 2 , 0
                          346.23          891.42
Permanent Ineff=
       F       F
Bank Sta=300.7,311.1
XS Rating Curve= 0 ,0
Exp/Cntr(USF)=0,0
Exp/Cntr=0.3,0.1

Type RM Length L Ch R = 1 ,3995    ,500,500,500
XS GIS Cut Line= 6
1669791.54479918398876.7159960871669712.77264701398927.975408003
1669636.92929475398971.6524860111669483.40926059399055.655926928
1669340.85442759 399133.658067511669264.66330701399189.476525426
#Sta/Elev= 30
       0 1068.36      28 1055.72    77.5  1018.8    94.7 1010.61   113.2 1003.66
   140.9  983.04   151.2  979.97     164  973.12   203.4     948   218.1  937.13
   232.6  930.53   241.7  923.62   250.8  913.02   265.3   901.9     275  891.04
   287.3  879.73   294.7  875.01   302.2  871.95   310.1  871.41   315.1  871.94
   324.2  875.37   366.7  875.28   401.3  876.71   460.6  875.43     501  877.82
   506.2  879.62   519.9  887.49   590.3  909.89   599.3  914.17   613.5  923.78
#Mann= 6 ,-1,0
       0      .1       0   211.5     .06       0   302.2    .045       0
   315.1     .06       0   316.5      .1       0   511.5     .05       0
Bank Sta=302.2,315.1
XS Rating Curve= 0 ,0
Exp/Cntr(USF)=0,0
Exp/Cntr=0.3,0.1

Type RM Length L Ch R = 1 ,3495    ,625.8,625.8,625.8
XS GIS Cut Line= 6
1669148.03296284398516.474918678 1669102.7876465398610.865805998
1669088.57934159398701.4883281741669095.20006326398776.737849593
1669131.98706317398949.8336320071669143.89747243399138.536666676
#Sta/Elev= 30
       0  959.08    26.7  945.04    48.9  936.58    84.3  916.28   104.7  906.77
   146.9  888.87     159  882.78   167.1  880.02     182  877.35   247.7  874.12
   267.7   872.4   275.9  870.88   304.7  869.59   308.8  869.03   316.8864.9714
   321.1  864.41   329.4     865     342   867.2   366.4  867.52   374.6  868.64
   411.2  868.94   431.5  870.25   439.6  872.08     449  875.35   463.8  883.32
   487.8  893.89   511.9  898.47     564  914.81   596.1  931.87   638.1  948.77
#Mann= 6 ,-1,0
       0      .1       0   316.8    .045       0   329.4      .1       0
  331.94     .07       0  421.94     .06       0  431.94      .1       0
Bank Sta=316.8,329.4
XS Rating Curve= 0 ,0
Exp/Cntr(USF)=0,0
Exp/Cntr=0.3,0.1

Type RM Length L Ch R = 1 ,2869    ,265.9,265.9,265.9
XS GIS Cut Line= 2
1668796.40075127 398277.586527771668548.43838941398738.849846068
#Sta/Elev= 30
       0 1008.19      17  993.91    48.8  972.92    66.9  956.86    85.1     943
    93.5   937.7   118.9  924.97   130.5  917.61   147.1  909.58   157.8  901.17
   173.7  892.96   182.6   887.2   203.2  867.74     215  859.51   220.2  857.07
   226.9  855.89   230.4  855.47   235.9855.9014     244  860.05   253.4  857.37
   277.1  859.51     344  861.25   366.7  860.99   393.9  862.44   416.6  865.72
   424.8  868.71   439.5  876.69   471.1  898.54   510.4  917.08   523.7  925.68
#Mann= 7 ,-1,0
       0      .1       0     190     .08       0   226.9    .045       0
   235.9     .08       0     300     .06       0     350     .05       0
     410      .1       0
#XS Ineff= 1 ,-1
  266.57 523.688  865.56
Permanent Ineff=
       F
Bank Sta=226.9,235.9
XS Rating Curve= 0 ,0
Exp/Cntr(USF)=0,0
Exp/Cntr=0.3,0.1

Type RM Length L Ch R = 1 ,2603    ,43.2,43.2,43.2
XS GIS Cut Line= 6
1668468.84973178398029.2746787471668390.83688197398289.975847727
1668427.37454581398324.5385027061668459.96219193398406.501370226
1668541.92505945 398452.914078341668431.32456352 398670.16505249
#Sta/Elev= 30
       0  980.03    24.3     957    32.6   951.5      41  951.68    57.7  955.04
    74.4  954.48    95.3  950.45   145.4  935.53   182.9  915.79   237.2  895.32
   241.4  892.18   263.5  869.75   272.1  862.87   290.4  863.25   310.8   859.7
   322.4  859.21   335.3  854.88   359.9  854.12     372852.2312   378.4   851.9
     387  852.24   395.6  855.33   404.2  856.88   486.8  858.88   601.7  859.85
     641  863.12   658.3  867.99   694.2  887.75   725.6  907.32   749.9  917.56
#Mann= 9 ,-1,0
       0      .1       0     230     .06       0  352.42     .08       0
     372    .045       0     387     .08       0   466.3     .05       0
  506.08     .08       0  526.08     .05       0  716.08      .1       0
Bank Sta=372,387
XS Rating Curve= 0 ,0
Exp/Cntr(USF)=0,0
Exp/Cntr=0.3,0.1

Type RM Length L Ch R = 1 ,2560    ,155.3,155.3,155.3
XS GIS Cut Line= 6
1668436.75583787398045.5685018081668358.74298806398306.269670788
 1668395.2806519398340.8323257671668427.86829802398422.795193287
1668509.83116554398469.2079014011668399.23066961398686.458875551
#Sta/Elev= 30
       0  965.14    15.6  952.95    27.3  942.33    32.3  939.28    40.7  938.26
    61.6  940.29    90.8  935.04   173.2  904.87   195.2     898   203.5  891.96
   227.9  867.41   240.7  860.76   249.4  854.85   275.4  854.86   297.3  857.78
   308.7  854.94   330.7  854.64   350.4  851.55   356.5  850.88   362.9  851.54
   378.1  856.45   554.7  859.22   595.1  861.31     622  864.49   637.8  871.29
   662.4   884.6   691.3  903.74   703.2  907.51   721.5   915.7   749.9  933.32
#Mann= 7 ,-1,0
       0      .1       0     210     .06       0   350.4    .045       0
   362.9     .06       0  430.62     .08       0  440.62     .05       0
  676.08      .1       0
Bank Sta=350.4,362.9
XS Rating Curve= 0 ,0
Exp/Cntr(USF)=0,0
Exp/Cntr=0.3,0.1

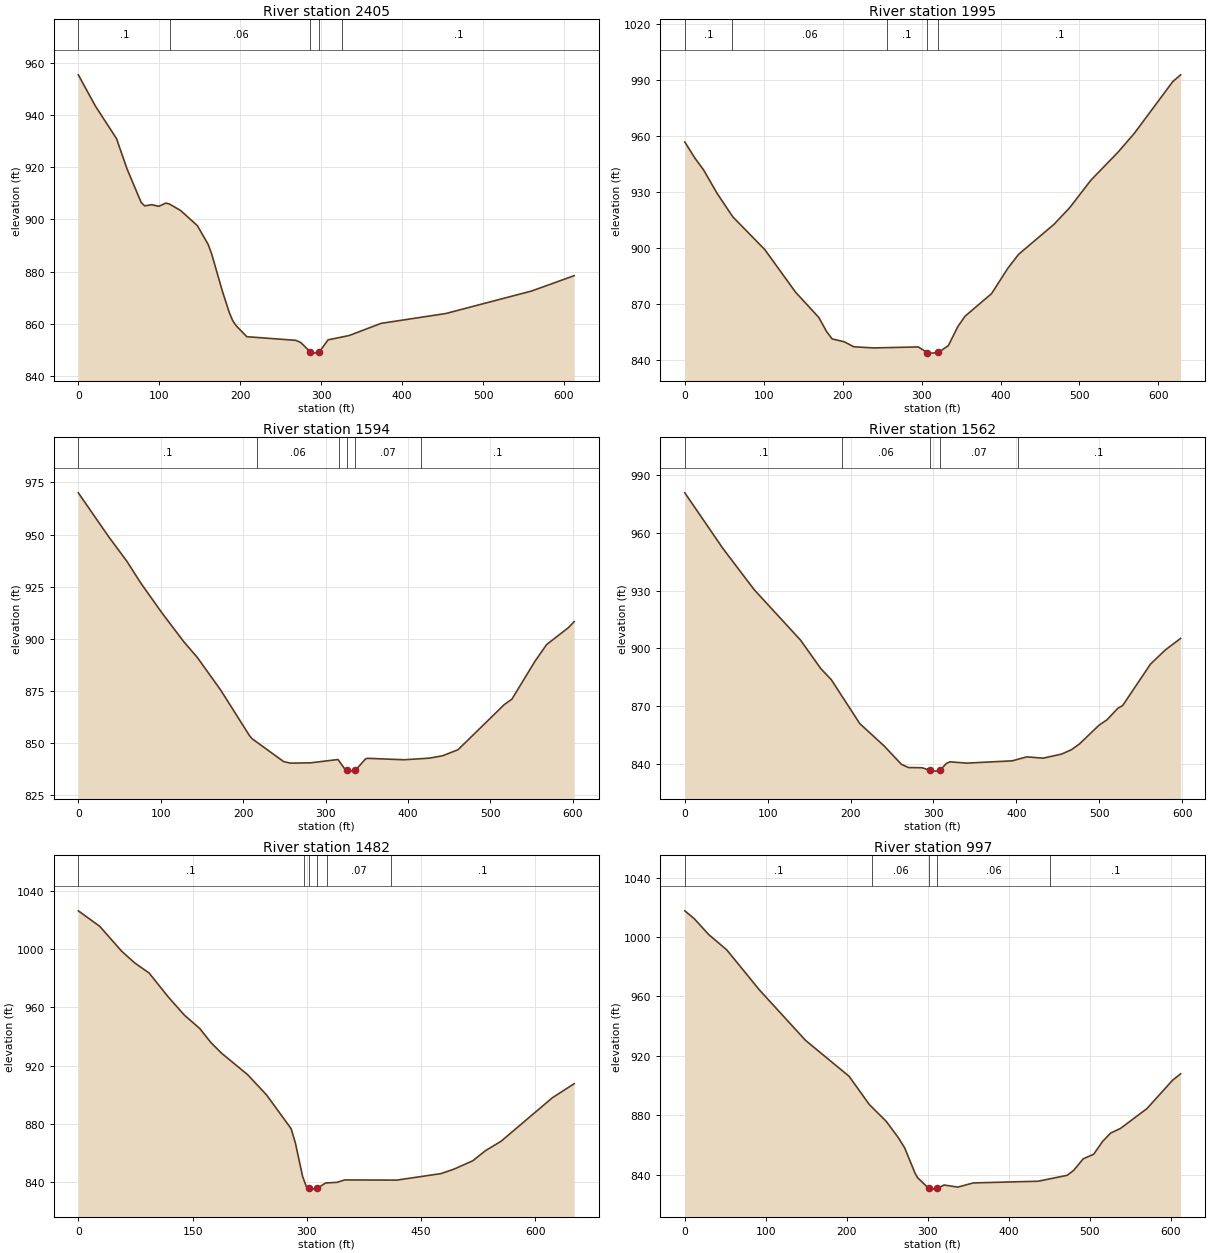
Type RM Length L Ch R = 1 ,2405    ,409.2,409.2,409.2
XS GIS Cut Line= 6
1668378.12235308398041.2763196341668340.97839851398127.396226134
1668306.40596109398207.8196217081668276.72787084 398276.73286971
1668236.70957818 398368.387542051668133.56969259398602.902164887
#Sta/Elev= 30
       0   955.4      21  943.47    47.1  931.01    60.2  919.35    77.6  906.52
      82  905.19    90.7  905.64    99.4  905.02   108.1  906.25   112.4  905.92
   126.4  903.42   147.1  897.61   160.3  890.48   164.7  886.83   177.8  872.69
   186.5  864.34   190.8  861.18   195.2   859.2   208.2  855.06   268.8  853.67
   274.9  852.82   286.5849.2755   291.1  848.77   297.9  849.29   308.5  853.85
   334.7  855.52     374  860.17   454.1  863.95   560.3  872.59   612.6  878.45
#Mann= 5 ,-1,0
       0      .1       0  113.79     .06       0   286.5    .045       0
   297.9     .06       0  326.36      .1       0
Bank Sta=286.5,297.9
XS Rating Curve= 0 ,0
Exp/Cntr(USF)=0,0
Exp/Cntr=0.3,0.1

Type RM Length L Ch R = 1 ,1995    ,401.4,401.4,401.4
XS GIS Cut Line= 6
1668249.60300118397912.3091322481668175.73175783397974.985844165
1668102.59049992 398026.428982751668032.72187325398053.695004344
1667866.19267876398109.4425962571667695.22976609398195.138947174
#Sta/Elev= 30
       0  956.84    12.7  948.28    23.9  941.84    40.9  929.37    60.8   916.8
   101.3  899.28   140.4  876.43   169.8  862.93   179.5   855.5   186.7  851.44
   202.2  849.89   214.1  847.25   239.3  846.62   295.8  847.16     307844.1758
   312.7  843.84   321.2  844.18   333.9  847.84   345.8  857.94     355  863.57
   388.7   875.7   409.2  889.21   422.9  896.71   467.8  912.79   487.9   921.8
   514.5  936.39   548.6  951.25   569.4  961.39   618.2  989.14   628.2  992.79
#Mann= 5 ,-1,0
       0      .1       0      60     .06       0   256.3      .1       0
     307    .045       0   321.2      .1       0
Bank Sta=307,321.2
XS Rating Curve= 0 ,0
Exp/Cntr(USF)=0,0
Exp/Cntr=0.3,0.1

Type RM Length L Ch R = 1 ,1594    ,31.9,31.9,31.9
XS GIS Cut Line= 4
 1668108.1069735397641.910269417 1667945.0481235397768.829884834
1667772.05838087397721.5330638151667587.58521371397833.380971662
#Sta/Elev= 30
       0     970    36.8  948.94    58.9  937.17    75.9  926.63     102   912.1
     128  898.54   144.4     891   172.9  875.26   207.5   853.6   210.9  851.99
   249.1  841.03   257.4  840.27   281.7  840.42   315.1  842.01   323.7  837.31
   325.6836.8887   331.4  836.44   336.1836.8106   348.6  842.32   350.9  842.59
   395.3  841.89     426  842.67     442   843.8   460.8  846.72   516.9  868.38
   526.2     871   554.1  889.13   568.3  897.19   594.9  905.35   601.7  908.19
#Mann= 6 ,-1,0
       0      .1       0  216.63     .06       0  316.63     .07       0
   325.6    .045       0   336.1     .07       0  415.97      .1       0
Bank Sta=325.6,336.1
XS Rating Curve= 0 ,0
Exp/Cntr(USF)=0,0
Exp/Cntr=0.3,0.1

Type RM Length L Ch R = 1 ,1562    ,80.3,80.3,80.3
XS GIS Cut Line= 4
1668088.42081434 397610.855427551667937.74851527397737.500065582
 1667780.2637111397689.9404057631667581.59979948397818.674498063
#Sta/Elev= 30
       0  980.67    46.1  951.74    83.7  930.43   139.4  904.38   164.2  889.42
   176.7  883.76   211.1  860.96   240.3  849.46   261.2  839.88   269.7  838.18
   286.3  838.08   295.2  836.79     303  836.32     308  836.84   315.5  840.28
   319.7  841.14   340.1  840.47   394.9  841.65   412.5  843.71   432.3  843.04
   454.4  845.15   466.4  847.42   476.1  850.43   499.7  860.15   509.3  862.95
   522.4  868.93   528.2  870.35   561.7   891.8   579.4  899.08   598.1  905.17
#Mann= 5 ,-1,0
       0      .1       0     190     .06       0   295.2    .045       0
     308     .07       0  401.34      .1       0
Bank Sta=295.2,308
XS Rating Curve= 0 ,0
Exp/Cntr(USF)=0,0
Exp/Cntr=0.3,0.1

Type RM Length L Ch R = 1 ,1482    ,484.4,484.4,484.4
XS GIS Cut Line= 6
1668026.00896017397406.9111929241667915.65058509397550.860380083
1667870.47711901397610.8294202541667787.95038117397673.304360926
1667608.78833793397723.7996667621667508.55067751397754.713646919
#Sta/Elev= 30
       0 1026.13    28.2 1015.46    56.7  998.55    73.8  990.51    92.9   983.5
     118  967.11   139.4  954.53   159.4  945.44     174  935.84     188  928.53
   222.2  913.81   247.1   899.9   279.4  876.73   285.1  866.66   294.5  843.93
   299.3   837.1   303.1835.8088   307.9  835.28   313.6   835.8   324.6  839.48
   339.7  839.94   349.7  841.58   418.1  841.46   476.2  845.93   492.9  848.92
     518  854.76   534.3  861.56   555.2  868.17   622.2  897.87     651  907.57
#Mann= 6 ,-1,0
       0      .1       0  296.46     .08       0   303.1    .045       0
   313.6     .08       0  326.46     .07       0  409.97      .1       0
Bank Sta=303.1,313.6
XS Rating Curve= 0 ,0
Exp/Cntr(USF)=0,0
Exp/Cntr=0.3,0.1

Type RM Length L Ch R = 1 ,997     ,268.1,268.1,268.1
XS GIS Cut Line= 6
1667850.60937659397102.6726281791667766.75685401397144.599053502
1667621.41232842397217.2708241791667531.96959393397261.992519513
1667386.62441218397334.663634002 1667302.7718896397376.589731261
#Sta/Elev= 30
       0 1017.63    11.7 1012.33    29.6 1001.63      52  991.26    92.2  964.37
   149.3  930.37     203  906.24   227.8  887.36   248.8  875.97   263.6  865.07
   271.6  858.13   284.5  840.95   287.6  838.03   301.4  830.81   306.9  830.32
   311.7   830.8   320.3  833.09   337.2  831.67   356.3  834.49   436.6  835.64
   472.4  839.62   480.3  842.91   492.2  850.74   505.1   853.8   516.1   862.4
     526  868.03   538.1  871.14   570.8  884.47   602.5  903.59   612.5  907.94
#Mann= 5 ,-1,0
       0      .1       0  231.25     .06       0   301.4    .045       0
   311.7     .06       0  451.25      .1       0
Bank Sta=301.4,311.7
XS Rating Curve= 0 ,0
Exp/Cntr(USF)=0,0
Exp/Cntr=0.3,0.1

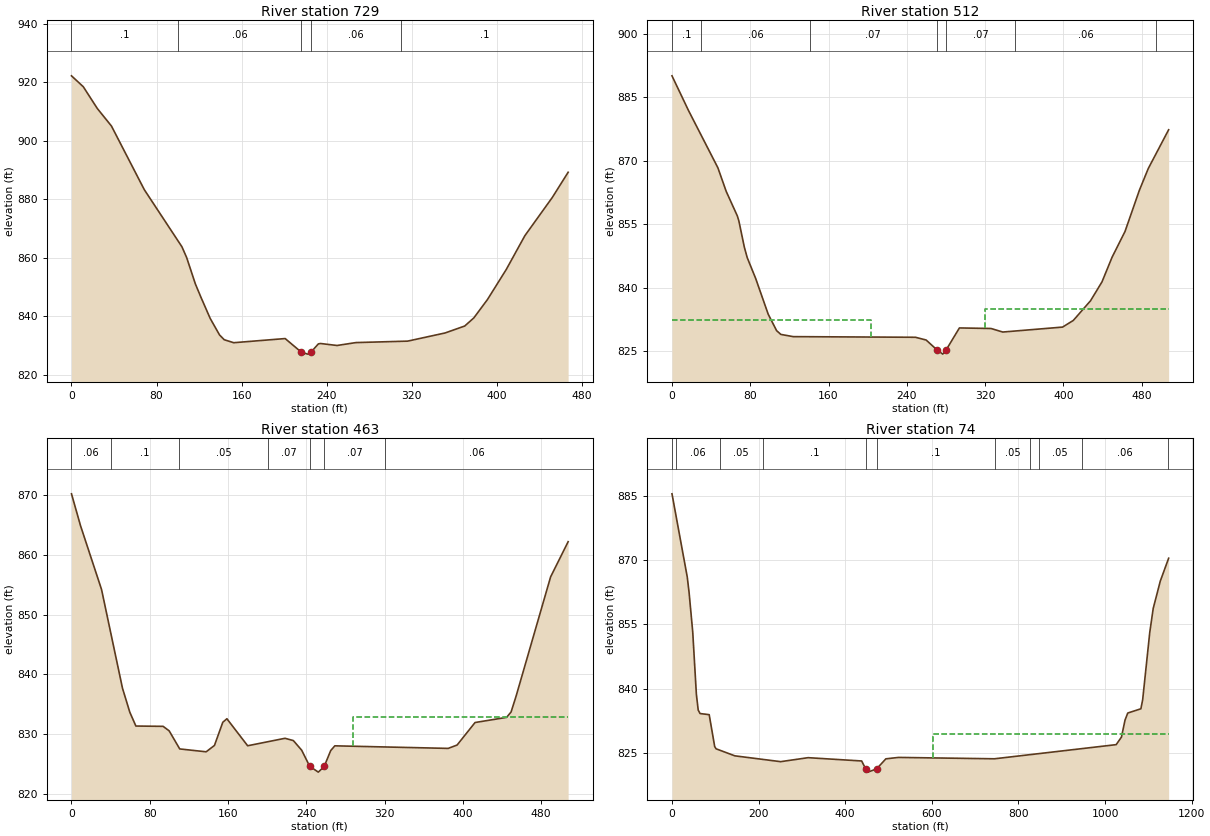
Type RM Length L Ch R = 1 ,729     ,217.6,217.6,217.6
XS GIS Cut Line= 2
1667634.12307564396918.8886675571667211.48743569 397118.01507484
#Sta/Elev= 30
       0  922.28    11.1  918.54    24.3  911.09    37.6  905.08    68.5  883.29
   103.9  863.74   108.3  860.09   116.5  851.06   121.6  846.61   130.5   839.2
   139.3  833.54   143.7  831.92   152.6   830.9     201  832.32   216.1  827.69
   222.2  826.99   225.3827.6638   232.2  830.49   234.2  830.63   249.8  829.95
   267.5  830.94   316.2  831.44   351.4  834.23   369.9  836.61   378.5   839.4
   391.3  845.68     409  855.98   426.5  867.55   452.3  880.63   467.2  889.26
#Mann= 5 ,-1,0
       0      .1       0     100     .06       0   216.1    .045       0
   225.3     .06       0     310      .1       0
Bank Sta=216.1,225.3
XS Rating Curve= 0 ,0
Exp/Cntr(USF)=0,0
Exp/Cntr=0.3,0.1

Type RM Length L Ch R = 1 ,512     ,48.2,48.2,48.2
XS GIS Cut Line= 4
1667575.79718997396816.6585246591667472.70172769396776.664595327
1667214.07431801396868.2062557991667153.63904702396974.856734018
#Sta/Elev= 30
       0  890.12    16.8  881.94    46.9  868.35    55.4  862.76    66.7  856.99
    68.3   855.8      74  849.49    76.9  847.06    85.5  842.15    98.3  833.69
   106.9  829.79   111.2   828.9   123.9  828.37   248.8  828.22   259.7  827.57
   270.7825.2493   276.7  824.23   280.2  825.25   293.7  830.43     326   830.3
     338  829.46   399.1  830.63   410.1  832.21   427.7  836.87   439.4  841.34
   449.7  847.17   462.9  853.26   477.6  863.02   486.7  868.18   507.5  877.35
#Mann= 7 ,-1,0
       0      .1       0      30     .06       0  140.58     .07       0
   270.7    .045       0   280.2     .07       0  350.58     .06       0
  494.93      .1       0
#XS Ineff= 2 , 0
          203.59  832.31     320             835
Permanent Ineff=
       F       F
Bank Sta=270.7,280.2
XS Rating Curve= 0 ,0
Exp/Cntr(USF)=0,0
Exp/Cntr=0.3,0.1

Type RM Length L Ch R = 1 ,463     ,389.2,389.2,389.2
XS GIS Cut Line= 4
1667548.69019342 396777.108972321667445.59473114396737.115042988
1667186.96732146396828.6567034591667126.53205047396935.307181678
#Sta/Elev= 30
       0   870.2     9.2  864.88    30.7   854.2    52.1  837.68    59.6  833.66
    65.8  831.35    93.6   831.3    99.8  830.55   110.6  827.52   137.6  827.04
   146.1  828.11   154.6  831.98   158.8  832.57     180  828.05   218.2   829.3
   226.7  828.92   235.2  827.31   243.4824.6188   252.2  823.64   258.2824.5857
   264.9  827.25   269.1  828.04   384.9  827.61     394  828.17   412.4  831.94
   444.6   832.8   449.2   833.7   454.4   836.4   489.6  856.31   507.5  862.19
#Mann= 7 ,-1,0
       0     .06       0      40      .1       0     110     .05       0
  200.58     .07       0   243.4    .045       0   258.2     .07       0
  320.58     .06       0
#XS Ineff= 2 , 0
                          288.14          832.87
Permanent Ineff=
       F       F
Bank Sta=243.4,258.2
XS Rating Curve= 0 ,0
Exp/Cntr(USF)=0,0
Exp/Cntr=0.3,0.1

Type RM Length L Ch R = 1 ,74      ,,,
XS GIS Cut Line= 4
1667616.21009751396769.7992044611667494.29597061396414.893635017
1667177.31924065396540.8715661551667096.04315604396963.507206103
#Sta/Elev= 30
       0  885.41    35.2  866.04    39.4  862.47    47.9  853.19    56.3  838.68
    60.5     835    64.8  834.17    85.9  833.91    98.6  826.47   101.8  825.95
   145.1  824.31   250.9  822.95   314.3  823.88   437.9  823.11   447.3821.2585
   452.1  820.51   472.3  821.25   493.8  823.61     523  823.94   744.5  823.62
  1025.6  826.92  1037.8  828.69    1046  832.64  1052.3  834.29  1082.6  835.28
  1086.7  837.36  1103.1  853.08  1111.1  858.69  1127.4  865.05  1146.7  870.39
#Mann= 11 ,-1,0
       0      .1       0      10     .06       0     110     .05       0
     210      .1       0   447.3    .045       0   472.3      .1       0
  746.35     .05       0  826.35     .06       0  846.35     .05       0
  946.35     .06       0 1146.35      .1       0
#XS Ineff= 2 , 0
                          602.16          829.32
Permanent Ineff=
       F       F
Bank Sta=447.3,472.3
XS Rating Curve= 0 ,0
Exp/Cntr(USF)=0,0
Exp/Cntr=0.3,0.1
LCMann Table=0

Chan Stop Cuts=-1
Use User Specified Reach Order=0
Composite Channel Slope=5